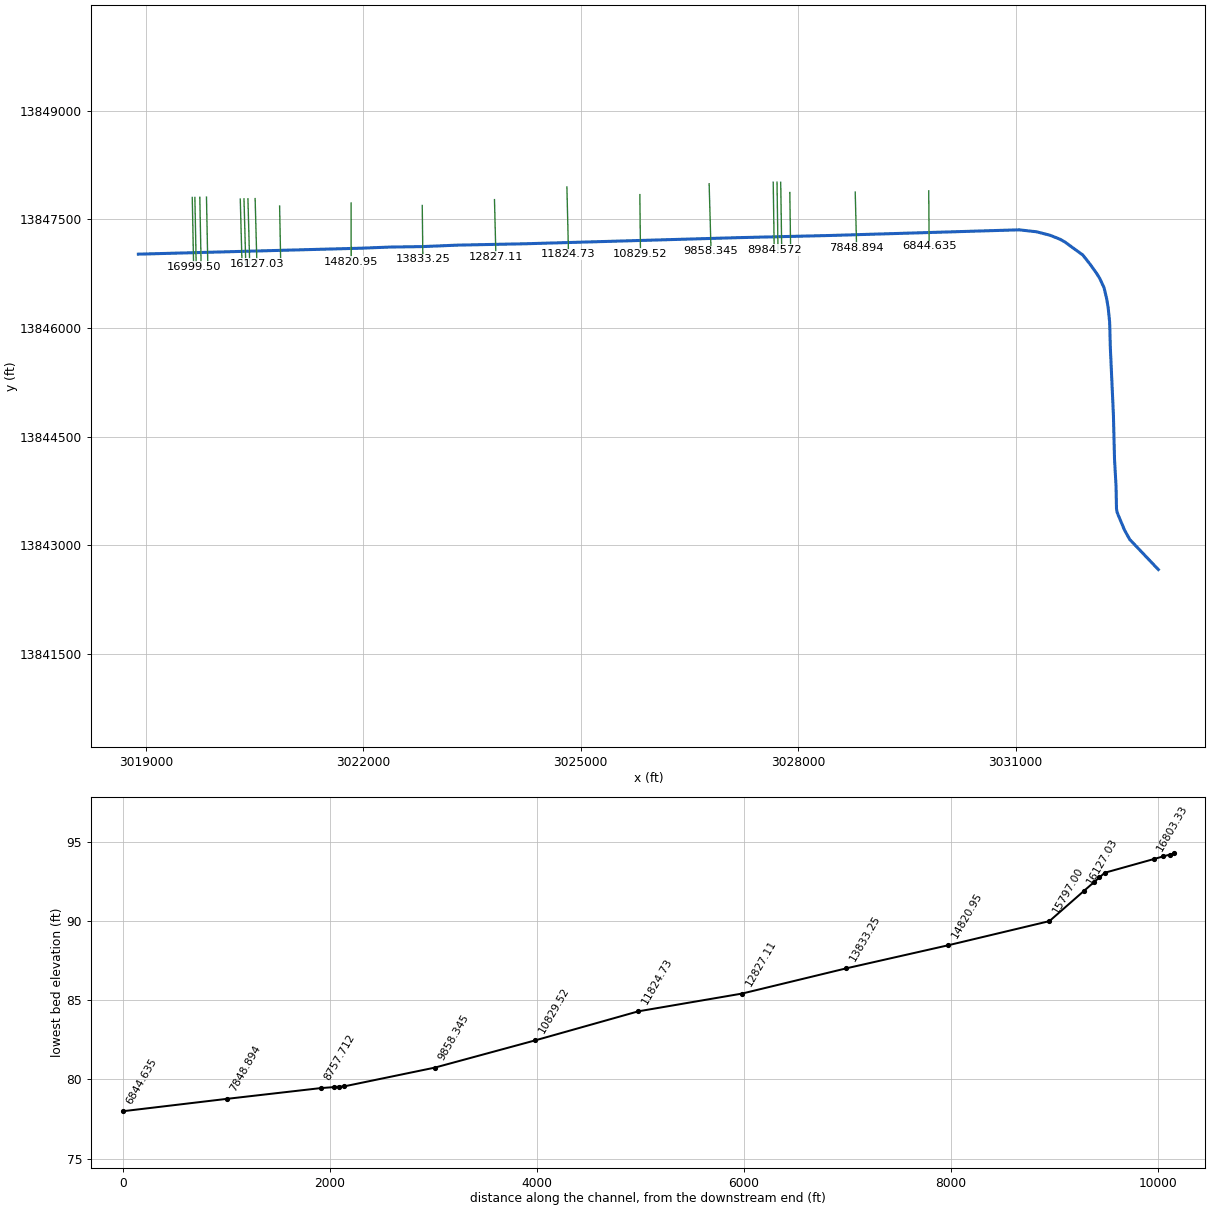
--- W170-00-00.prj (project) ---

Proj Title=W170-00-00
Current Plan=p02
Default Exp/Contr=.3,.1
English Units
Geom File=g01
Flow File=f01
Flow File=f02
Plan File=p01
Plan File=p02
Y Axis Title=Elevation
X Axis Title(PF)=Main Channel Distance
X Axis Title(XS)=Station
BEGIN DESCRIPTION:
Buffalo Bayou Watershed
Unnamed Tributary W170-00-00
HCFCD Unit W170-00-00
Flood Hazard & Floodway Model
10%, 2%, 1%, and 0.2% Events
Filename: W170.prj
Prepared by: JAS DATE: 05/23/2003
Reviewed by: Alem Gebriel, Joe Barrow
STATUS:  Final RAS
END DESCRIPTION:
DSS Export Rating Curves= 0
DSS Export Rating Curve Sorted= 0
DSS Export Volume Flow Curves= 0
DXF OffsetX= 0
DXF OffsetY= 0
DXF ScaleX= 1
DXF ScaleY= 10

--- W170-00-00.p02 (plan) ---

Plan Title=Floodway
Version=Version 3.0.1  Mar 2001
Short Identifier=Floodway0607
Geom File=g01
Flow File=f02
Subcritical Flow
K Sum by GR= 0
Std Step Tol= 0.01
Critical Tol= 0.01
Num of Std Step Trials= 20
Max Error Tol= 0.3
Flow Tol Ratio= 0.001
Split Flow NTrial= 30
Split Flow Tol= 0.02
Split Flow Ratio= 0.02
Log Output Level= 0
Friction Slope Method= 1
Unsteady Friction Slope Method= 2
Parabolic Critical Depth
Global Vel Dist= 0 , 0 , 0
Global Log Level= 0
CheckData=True
Encroach Param=-1 ,0,0, 2
Encroach River=W170-00-00
Encroach Reach=W170-00-00_0000
Encroach Node=16999.50
       1  742.81  783.07
Encroach Node=16963.37
       1  741.85  783.07
Encroach Node=16929
       4       1
Encroach Node=16895.43
       1  741.85  784.03
Encroach Node=16803.33
       1  741.85  785.94
Encroach Node=16332.21
       1  700.98  749.76
Encroach Node=16280.74
       1  700.07  747.95
Encroach Node=16253
       4       1
Encroach Node=16226.36
       1  700.07  747.95
Encroach Node=16127.03
       1  700.07  747.05
Encroach Node=15797.00
       1  585.73  630.37
Encroach Node=14820.95
       1  597.39  662.24
Encroach Node=13833.25
       1  537.59  596.17
Encroach Node=12827.11
       1  590.02  649.42
Encroach Node=11824.73
       1  737.17  805.12
Encroach Node=10829.52
       1   600.9  673.27
Encroach Node=9858.345
       1  726.57  798.48
Encroach Node=8984.572
       1  725.75   798.7
Encroach Node=8932.167
       1  725.72  797.21
Encroach Node=8906
       4       1
Encroach Node=8880.879
       1  724.56  794.47
Encroach Node=8757.712
       1  571.07  649.62
Encroach Node=7848.894
       1  541.29  630.48
Encroach Node=6844.635
       1  533.17  619.49
Encroach Node=5988.721
       1  476.46  568.19
Encroach Node=5111.837
       1  430.36  550.56
Encroach Node=4139.460
       1  450.95  567.61
Encroach Node=3308.081
       1  346.21  470.11
Encroach Node=2344.074
       1  478.94  601.89
Encroach Node=1344.937
       1  771.71  877.77
Encroach Node=614.193
       1  404.12  495.59
Encroach Node=195.587
       1  420.02  502.84
Encroach Node=134.394
       1  421.39   502.1
Encroach Node=120
       1  421.39   502.1
Encroach Node=106.132
       1  421.43  501.78
Encroach Node=21.824
       1  421.43  501.78
Computation Interval=1HOUR
Output Interval=1HOUR
Run HTab= 0
Run UNet= 0
Run PostProcess= 0
UNET Theta= 1
UNET ZTol= 0.02
UNET ZSATol= 0.05
UNET MxIter= 20
UNET MaxInSteps= 0
UNET DtIC= 0
UNET DtMin= 0
UNET MaxCRTS= 20
UNET WFStab= 2
UNET SFStab= 1
UNET WFX= 1
UNET SFX= 1
UNET Convert EG Bridges=-1
UNET Use Existing IB Tables=-1
Instantaneous Interval=1HOUR
Write IC File= 0
IC Time=0
Write Velocity= 0
Write Detailed= 0

--- W170-00-00.p01 (plan) ---

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Plan Title=FEMA Effective June 2007
Program Version=3.13
Short Identifier=FEMAeff0607
Geom File=g01
Flow File=f01
Unsteady Bridges Friction Slope Method= 1
Encroach Param=-1 ,0,0, 0
BEGIN DESCRIPTION:
10-, 50-, 100-, and 500-year floodplain model.
END DESCRIPTION:
UNET Theta Warmup= 1
UNET ZSATol= 0.1
UNET MaxInSteps= 20
UNET DSS MLevel= 4
UNET DZMax Abort= 100
UNET Froude Reduction=False
UNET Froude Limit= 1
UNET Froude Power= 10
DSS File=dss
Echo Input=False
Echo Output=False
Detailed Automatic Start=False, 10

--- W170-00-00.f02 (steady flow) ---

Flow Title=Floodway
Program Version=3.13
Number of Profiles= 2
Profile Names=1PCT_100_YR,1PCT_Floodway_100yrFW
River Rch & RM=W170-00-00,W170-00-00_0000      ,16999.50
     410     410
River Rch & RM=W170-00-00,W170-00-00_0000      ,14820.95
     541     541
River Rch & RM=W170-00-00,W170-00-00_0000      ,11824.73
     714     714
River Rch & RM=W170-00-00,W170-00-00_0000      ,8757.712
     893     893
River Rch & RM=W170-00-00,W170-00-00_0000      ,5988.721
    1051    1051
River Rch & RM=W170-00-00,W170-00-00_0000      ,3308.081
    1234    1234
River Rch & RM=W170-00-00,W170-00-00_0000      ,614.193
    1276    1276
River Rch & RM=W170-00-00,W170-00-00_0000      ,134.394
    1313    1313
Boundary for River Rch & Prof#=W170-00-00,W170-00-00_0000      , 1
Up Type= 0
Dn Type= 3
Dn Slope=0.002
Boundary for River Rch & Prof#=W170-00-00,W170-00-00_0000      , 2
Up Type= 0
Dn Type= 3
Dn Slope=0.002
DSS Import GetInterval= 0
DSS Import GetPeak= 0
DSS Import FillOption= 0

--- W170-00-00.f01 (steady flow) ---

Flow Title=FEMA Effective June 2007
Program Version=3.13
Number of Profiles= 4
Profile Names=10PCT_10yr,2PCT_50yr,1PCT_100yr,0.2PCT_500yr
River Rch & RM=W170-00-00,W170-00-00_0000 ,16999.50
     218     342     410     615
River Rch & RM=W170-00-00,W170-00-00_0000 ,14820.95
     288     451     541     812
River Rch & RM=W170-00-00,W170-00-00_0000 ,11824.73
     380     596     714    1072
River Rch & RM=W170-00-00,W170-00-00_0000 ,8757.712
     475     745     893    1339
River Rch & RM=W170-00-00,W170-00-00_0000 ,5988.721
     559     877    1051    1576
River Rch & RM=W170-00-00,W170-00-00_0000 ,3308.081
     657    1030    1234    1852
River Rch & RM=W170-00-00,W170-00-00_0000 ,614.193
     679    1065    1276    1915
River Rch & RM=W170-00-00,W170-00-00_0000 ,134.394
     699    1096    1313    1970
Boundary for River Rch & Prof#=W170-00-00,W170-00-00_0000 , 1
Up Type= 0
Dn Type= 3
Dn Slope=0.002
Boundary for River Rch & Prof#=W170-00-00,W170-00-00_0000 , 2
Up Type= 0
Dn Type= 3
Dn Slope=0.002
Boundary for River Rch & Prof#=W170-00-00,W170-00-00_0000 , 3
Up Type= 0
Dn Type= 3
Dn Slope=0.002
Boundary for River Rch & Prof#=W170-00-00,W170-00-00_0000 , 4
Up Type= 0
Dn Type= 3
Dn Slope=0.002
DSS Import GetInterval= 0
DSS Import GetPeak= 0
DSS Import FillOption= 0

--- W170-00-00.g01 (geometry) ---

Geom Title=W170-00-00 June 2007
Program Version=3.11

River Reach=W170-00-00   ,W170-00-00_0000
Reach XY= 30
     3018896.765    13847019.304     3021971.575    13847101.576
     3022381.527    13847117.561     3022815.454    13847123.672
     3023302.036    13847143.888      3024235.71    13847162.693
     3027170.716    13847246.846      3028439.12    13847276.934
     3031048.327    13847354.975     3031287.622    13847328.178
     3031474.733    13847280.225      3031612.01     13847225.69
     3031675.948     13847189.96     3031926.526    13847008.021
     3032026.193    13846882.027     3032116.927    13846755.563
     3032161.119    13846684.103     3032220.355    13846556.229
     3032255.615    13846408.138     3032277.241    13846280.264
     3032297.456    13846084.221     3032307.329    13845725.513
      3032349.64    13844797.481     3032364.685    13844195.718
      3032386.31    13843807.393     3032391.952    13843506.511
     3032401.354    13843454.797     3032501.022    13843215.973
     3032573.891    13843083.867     3032969.269    13842667.804

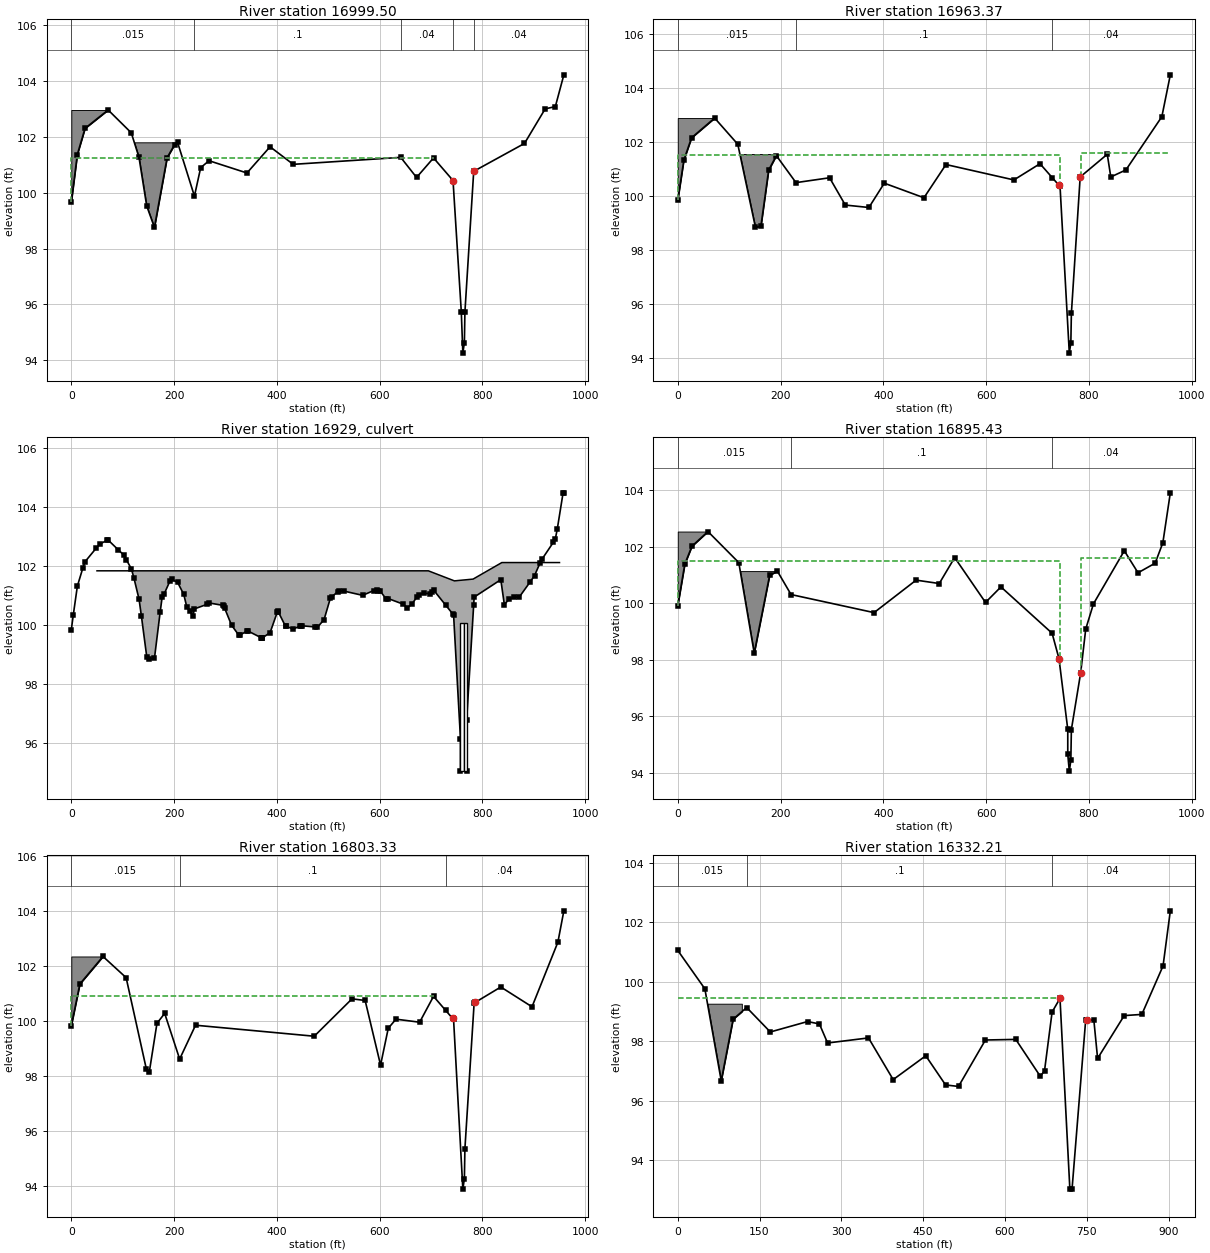
Type RM Length L Ch R = 1 ,16999.50,36.12,36.13,36.12
BEGIN DESCRIPTION:
Sta. 17000: North side of IH10 blocked
END DESCRIPTION:
XS GIS Cut Line= 3
     3019640.143    13847801.749     3019655.147    13847039.893
     3019659.015    13846843.468
#Sta/Elev= 30
       0   99.66   11.71  101.37   26.71  102.31   71.72  102.97  116.73  102.15
  131.73  101.27  146.73   99.53  161.74   98.76  186.46  101.26  201.18  101.73
  206.75  101.81  239.62   99.88  251.75   100.9  267.99  101.15  341.77  100.71
  386.78  101.65  431.79  101.02  641.06  101.27  671.84  100.55  704.87  101.25
  742.81  100.44  758.91   95.73  761.91   94.25  764.91   94.63  765.93   95.72
  783.07  100.77  881.88  101.77  922.12  103.01  941.89  103.09  958.47  104.23
#Mann= 5 ,-1 , 0
       0    .015       0  239.62      .1       0  641.06     .04       0
  742.81     .04       0  783.07     .04       0
#XS Ineff= 2 , 0
       0  704.87  101.25               0
Permanent Ineff=
       F       F
#Block Obstruct= 2 ,-1
       0   71.72  102.97     120  206.75  101.81
Bank Sta=742.81,783.07
XS Rating Curve= 0
Exp/Cntr=0.5,0.3

Type RM Length L Ch R = 1 ,16963.37,67.94,67.94,67.94
BEGIN DESCRIPTION:
Sta. 16963: Survey Data from Sta. 16999.50 used, adjusted for slope
North side of IH10 blocked
END DESCRIPTION:
XS GIS Cut Line= 3
     3019676.269    13847801.844     3019691.273    13847039.987
     3019695.141    13846843.562
#Sta/Elev= 30
       0   99.84    11.8  101.32   26.81  102.15   71.81  102.88  116.82  101.91
  151.12   98.84  161.83   98.88  176.83  100.95  191.84  101.49  230.03  100.49
  295.41  100.67  326.02   99.66  371.93   99.57  401.88  100.47  479.06   99.93
   521.9  101.16  654.12  100.59  704.87  101.19  728.44  100.68  741.85  100.39
  743.88  100.35  761.91   94.18  764.91   94.56  765.93   95.65  783.07   100.7
  835.78  101.54  842.64   100.7  872.06  100.96  941.98  102.93  958.47  104.48
#Mann= 3 ,-1 , 0
       0    .015       0  230.03      .1       0  728.44     .04       0
#XS Ineff= 2 , 0
       0   743.3   101.5   783.8       0   101.6
Permanent Ineff=
       F       F
#Block Obstruct= 2 ,-1
       0   71.81  102.88     120  195.26  101.55
Bank Sta=741.85,783.07
XS Rating Curve= 0
Exp/Cntr=0.5,0.3

Type RM Length L Ch R = 2 ,16929   ,,,
BEGIN DESCRIPTION:
Structure 3: Bridge/Culvert @ Barker-Clodine Road
END DESCRIPTION:
Bridge Culvert--1,0,-1,-1, 0
Deck Dist Width WeirC Skew NumUp NumDn MinLoCord MaxHiCord MaxSubmerge Is_Ogee
14,42,2.6,0, 7, 7, , , 0.95, 0, 0,0,,
      50   694.8   745.5   781.8   837.8     900     950
  101.84  101.84   101.5  101.56  102.12  102.12  102.12
       0       0       0       0       0       0       0
      50   694.8   745.5   781.8   837.8     900     950
  101.84  101.84   101.5  101.56  102.12  102.12  102.12
       0       0       0       0       0       0       0
BR Coef=-1 , 1 , 1 ,1.25, 0 ,,,0.8,0,2,0,
WSPro=,,,, 1 ,,,, 0 ,,,, 0 ,,,,-1 ,-1 ,-1 , 0 , 0 , 0 , 0 , 0
Multiple Barrel Culv=2,5,6,42,0.015,0.5,1,10,1,95.06,94.95, 2,Culvert #1  , 0 ,14
   760.3   760.3   766.8   766.8
Culvert Bottom n=0.015
BR U #Sta/Elev= 101
       0   99.84    3.99  100.36    11.8  101.32   22.71  101.95   26.81  102.15
   48.13   102.6   56.81  102.76   69.54  102.87   71.81  102.88   90.86  102.56
  101.82  102.38  106.98  102.22  116.82  101.91  121.69  101.61  131.83  100.88
  136.41  100.31  146.83   98.93  151.12   98.84  161.83   98.88  172.97  100.45
  176.83  100.95  180.55  101.05  191.84  101.49  195.26  101.55  206.84  101.45
  218.89  101.04  224.69  100.62  230.03  100.49  236.85  100.31   239.4  100.55
   264.8  100.71  268.83  100.75  295.41  100.67  296.86  100.65  298.25  100.58
  311.86     100  326.02   99.66  327.68   99.66  341.87    99.8   342.9   99.81
  369.03   99.58  371.82   99.57  371.87   99.57  371.93   99.57  386.88   99.75
  401.24  100.46  401.88  100.47  402.54  100.46  416.88   99.96  417.84   99.96
  431.88   99.87  445.38   99.97  446.89   99.97  448.45   99.98  474.81   99.94
  479.06   99.93   491.9  100.19  504.24  100.92   506.9  100.96  518.95  101.14
   521.9  101.16   531.5  101.15  566.91  101.01  588.28  101.17  594.69  101.18
  596.92  101.16  601.49  101.15  611.92   100.9   616.8   100.9  646.02  100.71
  654.12  100.59  662.71  100.71  671.93  100.94   676.4  101.03  686.93  101.08
  697.67  101.06  701.94  101.11  704.87  101.19  728.44  100.68  741.85  100.39
  743.88  100.35   757.3   96.16   757.3   95.06   769.3   95.06   769.3   96.79
  783.07   100.7  783.91  100.95  835.78  101.54  842.64   100.7  851.96  100.88
  861.67  100.94  872.06  100.96  892.28  101.45  901.49  101.68  911.98   102.1
   916.2  102.24  938.19  102.81  941.98  102.93  945.63  103.25  956.99  104.48
  958.47  104.48
BR U #Mann= 3
       0    .015  230.03      .1  728.44     .04
BR D #Sta/Elev= 114
       0   99.92   13.74  101.39   27.55  102.02   28.74  102.06   56.98  102.51
   58.75  102.54   60.59  102.53   73.75  102.52   98.58   102.1  103.76  102.01
  115.83  101.56  118.76  101.44  121.81  101.17  133.76  100.19     143   99.06
  148.77   98.24  154.42    98.6  163.77   99.49  174.69  100.73  178.77  100.99
  183.02   101.1  193.78  101.14  204.11  100.59  208.78  100.44  213.63  100.41
  220.45  100.31  223.78  100.26  233.54  100.47  238.78  100.47  251.92  100.35
  253.79  100.34  255.68  100.35  268.79  100.43  281.73  100.12  296.78  100.14
   313.8  100.27  317.85  100.23  339.97   99.97  347.56   99.88   358.4   99.69
  369.85   99.63  381.98   99.67  392.13  100.02  403.82   99.93   410.1   99.91
  418.82   99.99  437.34  100.57  448.82  100.66  454.24  100.64  463.83  100.82
  473.87  100.86  493.83  100.61  504.41   100.8  508.84   100.7  519.72  101.08
  525.84  101.43  538.84  101.62  542.51  101.47  553.85  101.26  557.23  100.95
  568.85  100.96  580.94  100.45  583.85  100.45  586.65  100.46  598.85  100.03
  601.37  100.17  626.85  100.53  628.86  100.58  630.79  100.42  643.86   99.98
  657.46   99.75  658.87   99.72  672.76   99.48  674.93   99.45  703.37   99.18
  703.87   99.18  718.68   98.95  718.88   98.95  728.44   98.94  728.95   98.94
  733.79   98.93  733.88   98.92  733.98   98.91  741.85   98.04   757.3   95.78
   757.3   94.95   769.3   94.95   769.3   95.88   778.4   96.67  779.89    96.9
  784.03   97.54  793.89   99.09   795.2   99.14  808.89   99.98  822.06  100.31
   823.9  100.36   825.8  100.37   838.9  100.62  841.11  100.73   853.9  101.32
  856.41  101.37  868.91  101.86  874.97  101.93  883.91   101.4  895.63  101.08
  898.91  101.08  902.33  101.17  913.92  101.36  925.06  101.36  928.92  101.42
  932.94   101.6  943.92  102.14  954.48  103.43  958.47  103.91
BR D #Mann= 3
       0    .015  220.45      .1  728.44     .04
BC Design=,, 0 ,, 0 ,,,,,,
BC HTab HWMax=104.48

Type RM Length L Ch R = 1 ,16895.43,92.09,92.09,92.09
BEGIN DESCRIPTION:
Sta. 16895: Survey Data from Sta. 16999.50 used, adjusted for slope
North side of IH10 blocked
END DESCRIPTION:
XS GIS Cut Line= 3
     3019744.182    13847803.782     3019759.186    13847041.926
     3019763.054      13846845.5
#Sta/Elev= 30
       0   99.92   13.74  101.39   27.55  102.02   58.75  102.54  118.76  101.44
  148.77   98.24  178.77  100.99  193.78  101.14  220.45  100.31  381.98   99.67
  463.83  100.82  508.84   100.7  538.84  101.62  598.85  100.03  628.86  100.58
  728.44   98.94  741.85   98.04  758.91   95.54  758.91   94.65  761.91   94.06
  764.91   94.44  765.93   95.53  784.03   97.54  793.89   99.09  808.89   99.98
  868.91  101.86  895.63  101.08  928.92  101.42  943.92  102.14  958.47  103.91
#Mann= 3 ,-1 , 0
       0    .015       0  220.45      .1       0  728.44     .04       0
#XS Ineff= 2 , 0
       0   743.3   101.5   783.8       0   101.6
Permanent Ineff=
       F       F
#Block Obstruct= 2 ,-1
       0   58.75  102.54     120  193.78  101.14
Bank Sta=741.85,784.03
XS Rating Curve= 0
Exp/Cntr=0.5,0.3

Type RM Length L Ch R = 1 ,16803.33,470.86,471.12,471.42
BEGIN DESCRIPTION:
Sta. 16803: Survey Data from Sta. 16999.50 used, adjusted for slope
North side of IH10 blocked
END DESCRIPTION:
XS GIS Cut Line= 3
     3019836.228    13847806.725     3019851.232    13847044.869
       3019855.1    13846848.443
#Sta/Elev= 30
       0   99.83   16.68  101.35   61.69  102.35   106.7  101.58  146.14   98.25
  151.71   98.14  166.71   99.92  181.72  100.28  210.86   98.62  241.76   99.85
  472.77   99.45  546.27  100.81  571.79  100.75   601.8    98.4   616.8   99.74
   631.8  100.07  677.85   99.96  704.87   100.9  728.44  100.39  741.85   100.1
  743.88  100.06  761.91   93.89  764.91   94.27  765.93   95.36  783.91  100.66
  785.94  100.68  835.78  101.24  896.51  100.52  946.86  102.87  958.47  104.01
#Mann= 3 ,-1 , 0
       0    .015       0  210.86      .1       0  728.44     .04       0
#XS Ineff= 2 , 0
       0  704.87   100.9  835.78       0  101.24
Permanent Ineff=
       F       F
#Block Obstruct= 1 ,-1
       0   59.76  102.35
Bank Sta=741.85,785.94
XS Rating Curve= 0
Exp/Cntr=0.3,0.1

Type RM Length L Ch R = 1 ,16332.21,51.47,51.48,51.48
BEGIN DESCRIPTION:
Sta. 16332
END DESCRIPTION:
XS GIS Cut Line= 3
     3020302.562    13847779.716      3020322.19    13847056.743
     3020327.078    13846876.728
#Sta/Elev= 30
       0  101.05   49.69   99.76    79.7   96.67  101.49   98.74  126.46   99.13
  169.73   98.31  237.99   98.66  259.77   98.58  274.77   97.94   349.8   98.11
  395.07   96.71  454.84   97.51  491.17   96.53  514.86   96.48  564.22   98.04
   619.9   98.06  664.92   96.82  672.64   97.01  686.52   98.98  700.98   99.44
  719.06   93.04  723.09   93.03  748.05    98.7  749.76    98.7  763.02   98.72
  769.96   97.42  818.73   98.86  851.05    98.9     890  100.53  903.32  102.38
#Mann= 3 ,-1 , 0
       0    .015       0  126.46      .1       0  686.52     .04       0
#XS Ineff= 2 , 0
       0  701.01   99.44  748.05       0    98.7
Permanent Ineff=
       F       F
#Block Obstruct= 2 , 0
       0   117.5   99.26               0
Bank Sta=700.98,749.76
XS Rating Curve= 0
Exp/Cntr=0.5,0.3

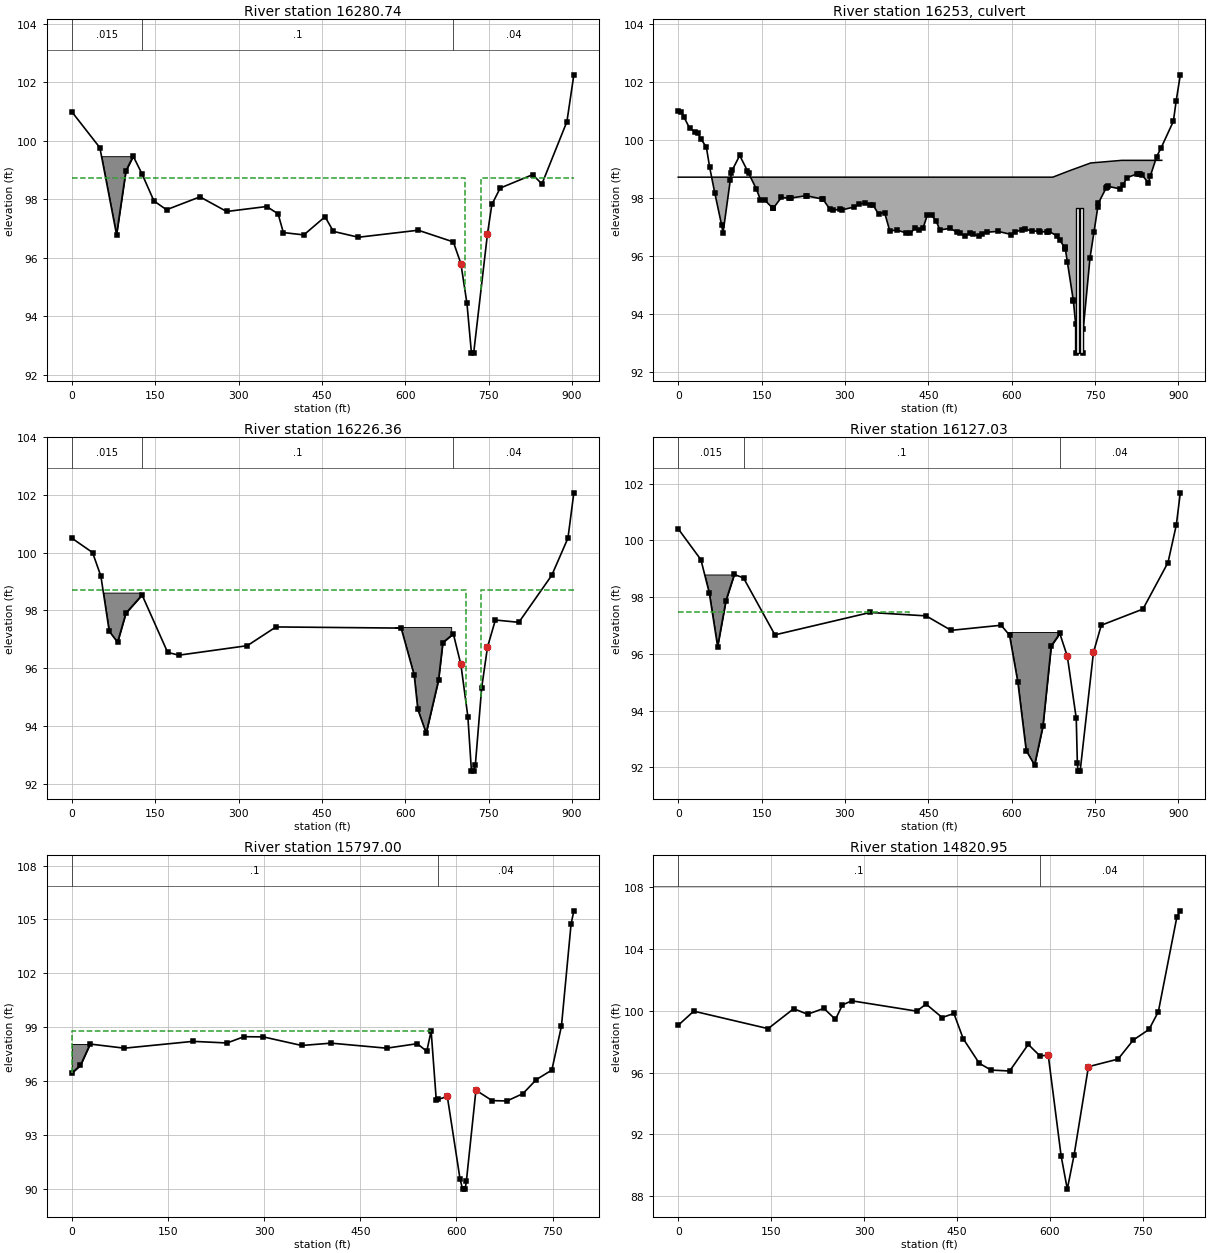
Type RM Length L Ch R = 1 ,16280.74,54.38,54.38,54.38
BEGIN DESCRIPTION:
Sta. 16821: Survey Data from Sta. 16332.22 used, adjusted for slope
END DESCRIPTION:
XS GIS Cut Line= 3
     3020354.031     13847780.57      3020373.66    13847057.598
     3020378.547    13846877.582
#Sta/Elev= 30
       0  100.99   50.54   99.76   80.56   96.79   97.42   98.97  110.57   99.47
  126.46   98.86  147.84   97.94  170.47   97.64  230.61   98.08  278.69   97.58
  350.66   97.75  371.23    97.5  380.67   96.86  417.51   96.78  455.69    97.4
   470.7    96.9  515.72    96.7  623.34   96.94  686.52   96.54  700.07    95.8
     711   94.44  719.0692.74693  723.0992.74043  747.95   96.82   755.8   97.82
  770.81   98.38  829.33   98.84  845.84   98.52  890.85  100.65  903.32  102.25
#Mann= 3 ,-1 , 0
       0    .015       0  126.46      .1       0  686.52     .04       0
#XS Ineff= 2 , 0
       0  707.35   98.72  736.15       0   98.72
Permanent Ineff=
       F       F
#Block Obstruct= 2 , 0
       0  110.57   99.47               0
Bank Sta=700.07,747.95
XS Rating Curve= 0
Exp/Cntr=0.5,0.3

Type RM Length L Ch R = 2 ,16253   ,,,
BEGIN DESCRIPTION:
Structure 4: Bridge/Culvert @ Harris County Annex 13
END DESCRIPTION:
Bridge Culvert--1,0,-1,-1, 0
Deck Dist Width WeirC Skew NumUp NumDn MinLoCord MaxHiCord MaxSubmerge Is_Ogee
7.5,40.5,2.6,0, 6, 6, , , 0.95, 0, 0,0,,
       0   673.8   703.6   742.1     798     870
   98.72   98.72   98.94   99.21    99.3    99.3
       0       0       0       0       0       0
       0   673.8   703.6   742.1     798     870
   98.72   98.72   98.94   99.21    99.3    99.3
       0       0       0       0       0       0
BR Coef=-1 , 1 , 1 ,1.25, 0 ,,,0.8,0,2,0,
WSPro=,,,, 1 ,,,, 0 ,,,, 0 ,,,,-1 ,-1 ,-1 , 0 , 0 , 0 , 0 , 0
Multiple Barrel Culv=2,5,6,40.5,0.015,0.5,1,10,1,92.65,92.51, 2,Culvert #1  , 0 ,7.5
  718.05  718.15  725.65  726.61
Culvert Bottom n=0.015
BR U #Sta/Elev= 108
       0  100.99    5.53  100.97    9.77  100.81   20.53  100.41   29.88  100.28
   35.54  100.23   41.35  100.02   50.54   99.76   56.56   99.06   65.55   98.19
   78.17   97.06   80.56   96.79    93.6   98.61   95.56   98.88   97.42   98.97
  110.57   99.47  124.45   98.94  126.46   98.86  140.58   98.31  147.84   97.94
  155.58   97.93  170.47   97.64  170.59   97.64  170.72   97.64  185.59   98.02
  199.68   97.99  201.08      98  202.59      98  230.61   98.08  232.42   98.07
  258.12   97.97  260.62   97.95  272.73   97.62  278.69   97.58  290.63   97.61
  294.11   97.59  316.56   97.69  324.96   97.79  335.65   97.82  345.77   97.76
  350.66   97.75  360.38   97.45  371.23    97.5  380.67   96.86  392.99    96.9
  410.68   96.79  417.51   96.78  425.68   96.96  433.43   96.91  440.69   96.98
  448.04    97.4  455.69    97.4  463.78   97.22   470.7    96.9   488.2   96.95
  500.71   96.84  506.47   96.78  515.72    96.7  525.48    96.8  530.72   96.76
   540.9   96.68  545.73   96.75  554.63   96.82  575.74   96.85  599.27   96.74
  605.75   96.82  618.02   96.91  623.34   96.94  635.76   96.86  648.87   96.86
  650.77   96.83   664.3   96.84  665.77   96.83  667.17   96.85  680.78    96.7
  686.52   96.54  695.14    96.3  695.78   96.29  696.39   96.25  700.07    95.8
  710.79   94.47     711   94.44  715.05   93.64  715.05   92.65  728.65   92.65
  728.65   93.47   740.8   95.93  747.95   96.82  754.82   97.68   755.8   97.82
  769.43   98.33  770.81   98.38  771.53   98.39  773.81    98.4  794.35   98.32
  800.82   98.46  807.12    98.7  825.05   98.83  829.33   98.84  830.83   98.84
  833.96   98.81  845.84   98.52  849.39   98.76  860.84   99.43  869.01   99.74
  890.85  100.65  895.95  101.36  903.32  102.25
BR U #Mann= 3
       0    .015  126.46      .1  686.52     .04
BR D #Sta/Elev= 99
       0  100.51   12.05   100.3    19.7  100.25   27.99  100.12   37.39  100.01
    46.3   99.48    52.4   99.19   60.91   98.18    67.4   97.28   70.79   97.33
   82.41    96.9      86   97.14   97.41   97.91  105.11   98.13  112.42   98.41
  119.34    98.5  123.33   98.62  126.47   98.54  127.43   98.51  139.55   98.07
  146.85    97.7  157.44   97.08  166.81    96.8  172.44   96.55  177.78   96.51
  192.48   96.45  212.16    96.6  217.46   96.65  228.51   96.79  232.46   96.82
  236.21   96.78  247.47   96.58  256.57   96.61  274.78   96.88  280.04   96.92
  292.49    96.9  300.98    96.8  307.49   96.74  315.79   96.78  329.39    96.9
   337.5   97.14  367.12   97.42  367.42   97.43  367.58   97.43  367.69   97.43
  367.86   97.43  417.15   97.32  427.54   97.39  448.53   97.42  480.78   97.39
  507.36   97.38  532.58   97.41  545.26   97.47  552.42   97.43  565.85   97.34
  572.22   97.39  581.36   97.43   592.6   97.39  598.69   96.83   607.6   96.49
  616.05   95.76  622.61   94.57  629.54   94.13  637.61   93.75  644.96   94.54
  659.87   95.59  667.62   96.89  674.48   96.99  682.63   97.44  686.52   97.19
  689.09   97.02  697.64   96.49  700.07   96.13  706.66   95.15  712.64   94.32
  715.15   93.58  715.15   92.51  729.61   92.51  729.61   93.71  737.51   95.32
  742.65   96.17  747.53   96.69  747.95   96.73  757.66   97.57  762.13   97.67
  783.78   97.83  787.67   97.86  799.21   97.61  804.34   97.59  817.68   97.84
  820.57    97.9  838.99   98.38     859   99.09  861.81   99.16  863.56   99.22
   877.7   99.71  879.01   99.78  892.71  100.51  903.32  102.08
BR D #Mann= 3
       0    .015  126.47      .1  686.52     .04
BC Design=,, 0 ,, 0 ,,,,,,
BC HTab HWMax=102.25

Type RM Length L Ch R = 1 ,16226.36,99.33,99.33,99.33
BEGIN DESCRIPTION:
Sta. 16226: Survey Data from Sta. 16332.22 used, adjusted for slope
END DESCRIPTION:
XS GIS Cut Line= 3
     3020408.377    13847782.423     3020428.005     13847059.45
     3020432.892    13846879.434
#Sta/Elev= 30
       0  100.51   37.39  100.01    52.4   99.19    67.4   97.28   82.41    96.9
   97.41   97.91  126.47   98.54  172.44   96.55  192.48   96.45  315.79   96.78
  367.42   97.43   592.6   97.39  616.05   95.76  622.61   94.57  637.61   93.75
  659.87   95.59  667.62   96.89  686.52   97.19  700.07   96.13  712.64   94.32
  719.0692.43705  723.0992.43055  726.0892.64255  737.51   95.32  747.95   96.73
  762.13   97.67  804.34   97.59  863.56   99.22  892.71  100.51  903.32  102.08
#Mann= 3 ,-1 , 0
       0    .015       0  126.47      .1       0  686.52     .04       0
#XS Ineff= 2 , 0
       0  709.65   98.72  736.11       0   98.72
Permanent Ineff=
       F       F
#Block Obstruct= 2 ,-1
  581.36  682.63   97.43       0  123.33   98.62
Bank Sta=700.07,747.95
XS Rating Curve= 0
Exp/Cntr=0.5,0.3

Type RM Length L Ch R = 1 ,16127.03,330.33,330.03,329.86
BEGIN DESCRIPTION:
Sta. 16127: Survey Data from Sta. 16332.22 used, adjusted for slope
END DESCRIPTION:
XS GIS Cut Line= 3
     3020507.647    13847785.859     3020527.275    13847062.886
     3020532.162    13846882.871
#Sta/Elev= 30
       0  100.41   40.83   99.32   55.84   98.15   70.84   96.26   85.85   97.88
  100.85    98.8  117.43   98.68  173.96   96.67  345.29   97.46  445.98   97.34
     491   96.83  580.99   97.01  596.03   96.66  611.04      95  626.05   92.59
  641.05   92.08  656.06   93.44  671.06   96.28  686.52   96.72  700.07   95.91
  716.08   93.73  718.06 92.1629  719.0691.87101  723.0991.86451  747.05   96.05
   761.1   97.01  836.12   97.58  881.14   99.22  896.15  100.55  903.32  101.68
#Mann= 3 ,-1 , 0
       0    .015       0  117.43      .1       0  686.52     .04       0
#XS Ineff= 2 , 0
       0  415.97   97.46               0
Permanent Ineff=
       F       F
#Block Obstruct= 2 ,-1
  591.35  683.41   96.77       0  100.85    98.8
Bank Sta=700.07,747.05
XS Rating Curve= 0
Exp/Cntr=0.3,0.1

Type RM Length L Ch R = 1 ,15797.00,976.85,976.04,975.21
BEGIN DESCRIPTION:
Sta. 15797
END DESCRIPTION:
XS GIS Cut Line= 2
     3020845.384    13847683.638     3020860.464    13846900.716
#Sta/Elev= 30
       0   96.44    13.6   96.88    28.6   98.06   82.04   97.83  189.12   98.21
  242.13   98.12  268.64   98.47  298.65   98.46  358.66   97.98   404.4   98.11
  491.07   97.83  538.69   98.08   553.7   97.66  560.49   98.79  568.49   94.94
  571.64   94.98  585.73   95.14  605.54   90.55  609.56   89.98  613.56      90
  615.56   90.46  630.37   95.49  655.55   94.91  678.76   94.89  703.72    95.3
  724.53   96.08  748.73   96.61  763.74   99.06  778.74  104.74  783.07  105.48
#Mann= 2 ,-1 , 0
       0      .1       0  571.64     .04       0
#XS Ineff= 2 , 0
       0  560.48   98.79               0
Permanent Ineff=
       F       F
#Block Obstruct= 2 , 0
       0    28.6   98.06               0
Bank Sta=585.73,630.37
XS Rating Curve= 0
Exp/Cntr=0.3,0.1

Type RM Length L Ch R = 1 ,14820.95,987.17,987.7,988.22
BEGIN DESCRIPTION:
Sta. 14281
END DESCRIPTION:
XS GIS Cut Line= 2
      3021831.89    13847725.109     3021833.147     13846914.54
#Sta/Elev= 30
       0   99.06   25.07   99.97  145.07   98.84  186.42  100.13  208.74   99.77
  235.07  100.15  253.81   99.44  265.07  100.37  280.07  100.64  385.07   99.97
  400.07  100.43  426.05   99.56  445.07   99.82  460.07   98.19  485.96    96.6
  505.07   96.16  535.07    96.1  565.07   97.82  583.61   97.09  597.39   97.11
   618.1   90.62   628.1   88.46   639.1   90.67  662.24   96.38   710.1   96.87
  734.56    98.1  760.07   98.79  775.07   99.93  805.07  106.07  810.57  106.46
#Mann= 2 ,-1 , 0
       0      .1       0  583.61     .04       0
#XS Ineff= 2 , 0
       0  565.07   97.82               0
Permanent Ineff=
       F       F
Bank Sta=597.39,662.24
XS Rating Curve= 0
Exp/Cntr=0.3,0.1

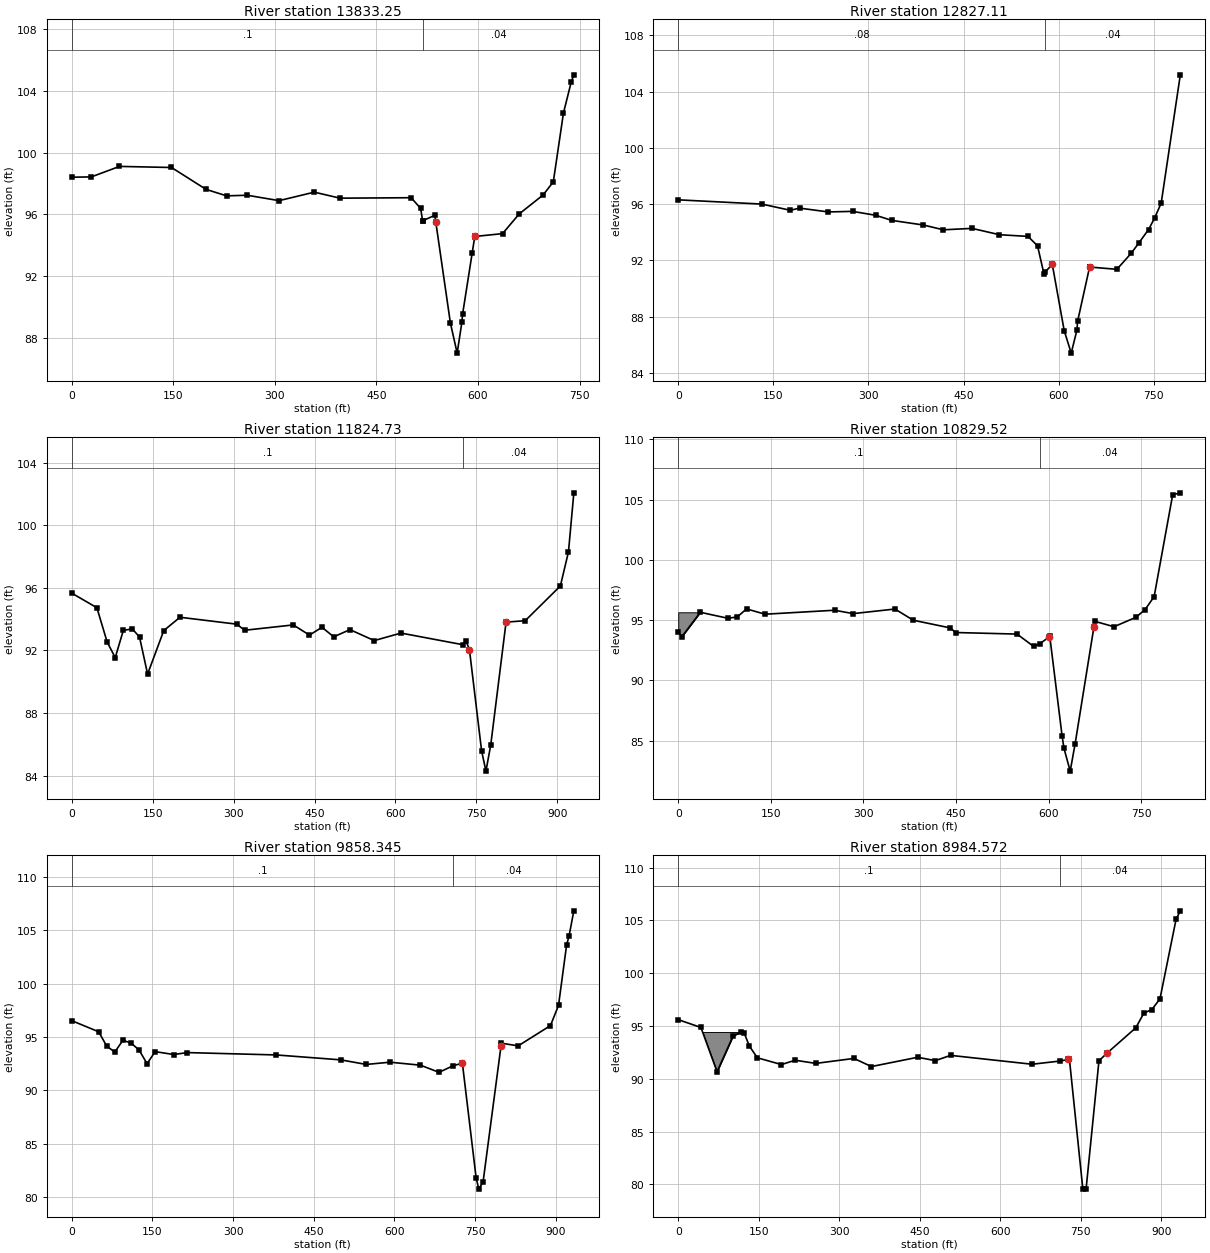
Type RM Length L Ch R = 1 ,13833.25,1005.35,1006.14,1006.76
BEGIN DESCRIPTION:
Sta. 13833
END DESCRIPTION:
XS GIS Cut Line= 2
      3022813.37    13847691.178     3022822.167    13846949.727
#Sta/Elev= 30
       0   98.41    28.9   98.43   70.47   99.11  147.28   99.04  198.34   97.62
   228.7    97.2  259.06   97.24  306.16   96.89   358.2   97.44  396.16   97.05
  501.17   97.08  515.22   96.39  518.18   95.58  519.05    95.6  536.18   95.94
  537.59   95.51  559.16   88.96  569.16      87  576.14      89  577.14   89.51
  591.33   93.49  595.17   94.56  596.17   94.57  636.18   94.75  660.83   96.03
  696.18   97.26  711.18   98.11  726.19  102.58   737.6  104.58   741.5  105.05
#Mann= 2 ,-1 , 0
       0      .1       0  519.05     .04       0
Bank Sta=537.59,596.17
XS Rating Curve= 0
Exp/Cntr=0.3,0.1

Type RM Length L Ch R = 1 ,12827.11,1002.44,1002.38,1002.38
BEGIN DESCRIPTION:
Sta. 12827
END DESCRIPTION:
XS GIS Cut Line= 2
      3023809.93    13847771.607     3023830.038    13846979.888
#Sta/Elev= 30
       0   96.31  131.61   96.01  176.62   95.57  191.62   95.72  236.64   95.45
  275.03   95.49  311.66   95.21  336.61   94.85  386.69   94.52  418.19   94.18
  463.55   94.28  506.73   93.83  551.74   93.71  566.75   93.04  576.75   91.07
  578.14   91.15  590.02   91.72  608.82   87.01  619.87   85.41  628.89   87.05
  629.89   87.66  648.91   91.54  649.42   91.53  691.94   91.37  714.53   92.51
  726.48   93.24  741.92    94.2  751.57   95.03  761.81   96.08  791.97   105.2
#Mann= 2 ,-1 , 0
       0     .08       0  578.14     .04       0
Bank Sta=590.02,649.42
XS Rating Curve= 0
Exp/Cntr=0.3,0.1

Type RM Length L Ch R = 1 ,11824.73,995.84,995.21,994.45
BEGIN DESCRIPTION:
Sta. 11825
END DESCRIPTION:
XS GIS Cut Line= 3
     3024809.494    13847945.583     3024812.827    13847795.787
     3024831.624    13847015.076
#Sta/Elev= 30
       0   95.66   46.55   94.73   65.56   92.54   80.56   91.54   95.56   93.28
  112.11   93.38  125.57   92.86  140.57   90.49  170.58   93.27  200.59   94.12
  305.62   93.68  320.63   93.29  410.65   93.63  440.66   92.98  463.82   93.48
  485.67   92.87  515.68   93.33   560.7   92.63  610.33   93.11     726   92.36
  730.79   92.61  737.17   92.06  759.74   85.59  767.78   84.29  776.71   85.96
  805.12   93.81  840.57    93.9   905.8   96.12   920.8    98.3  930.77  102.07
#Mann= 2 ,-1 , 0
       0      .1       0     726     .04       0
#XS Ineff= 2 , 0
       0  200.59   94.12               0
Permanent Ineff=
       F       F
Bank Sta=737.17,805.12
XS Rating Curve= 0
Exp/Cntr=0.3,0.1

Type RM Length L Ch R = 1 ,10829.52,970.36,971.18,972.27
BEGIN DESCRIPTION:
Sta. 10830
END DESCRIPTION:
XS GIS Cut Line= 2
     3025815.618    13847840.725     3025824.415    13847027.643
#Sta/Elev= 30
       0   94.04    5.68   93.61   35.68   95.65   80.69   95.15   95.69   95.27
  110.69   95.93  140.69   95.49  253.11   95.82  283.27   95.54     351   95.92
   380.7   94.99  440.71   94.35  449.18   93.97  548.73   93.84  575.71   92.81
  585.45   93.04   600.9    93.6  601.75   93.64  621.77   85.34  624.76   84.35
  634.78   82.46  642.76   84.73  673.27   94.45  674.73    94.9  705.73   94.45
  740.72   95.22  755.73   95.85  770.73   96.95  800.73   105.4  813.13  105.57
#Mann= 2 ,-1 , 0
       0      .1       0  585.45     .04       0
#Block Obstruct= 2 , 0
       0   35.68   95.65               0
Bank Sta=600.9,673.27
XS Rating Curve= 0
Exp/Cntr=0.3,0.1

Type RM Length L Ch R = 1 ,9858.345,874.4,873.77,872.86
BEGIN DESCRIPTION:
Sta. 9858
END DESCRIPTION:
XS GIS Cut Line= 3
     3026771.859    13847990.064     3026775.848    13847844.264
     3026798.354    13847056.547
#Sta/Elev= 30
       0   96.52   50.04   95.48   65.04   94.13   80.05   93.58   95.06   94.68
  110.06   94.43  125.07   93.78  140.07   92.49  155.08   93.62  189.61   93.35
   215.1   93.53  380.17   93.31  500.22   92.85  547.83   92.42  591.91   92.63
  648.62   92.35  683.16   91.68  709.76   92.31  726.57   92.53  752.13   81.79
  757.13   80.74   765.1   81.43  798.48   94.17  799.11   94.41  830.35   94.16
  890.38   96.06  905.38   97.95  920.39   103.6  924.96  104.46  933.89  106.81
#Mann= 2 ,-1 , 0
       0      .1       0  709.76     .04       0
Bank Sta=726.57,798.48
XS Rating Curve= 0
Exp/Cntr=0.3,0.1

Type RM Length L Ch R = 1 ,8984.572,52.4,52.4,52.4
BEGIN DESCRIPTION:
Sta. 8985
END DESCRIPTION:
XS GIS Cut Line= 4
     3027655.561    13848012.318     3027658.013    13847861.314
     3027666.722    13847256.545     3027669.305    13847077.174
#Sta/Elev= 30
       0    95.6   42.28   94.86   72.28   90.67  102.29   94.07  117.29   94.43
  123.26   94.29  132.29   93.12  147.29   91.99   192.3   91.35  217.74   91.76
  256.31   91.46  327.31   91.93  359.83   91.16  446.05   92.04  478.93   91.72
  507.33   92.22  659.14   91.38  710.79   91.68  725.75   91.83  728.67   91.86
  753.68   79.57  759.71   79.56  783.72   91.71   798.7   92.43  852.37   94.83
  867.37   96.22  882.37   96.56  897.37   97.57  927.37   105.1  935.25   105.9
#Mann= 2 ,-1 , 0
       0      .1       0  710.79     .04       0
#Block Obstruct= 2 , 0
       0  117.29   94.43               0
Bank Sta=725.75,798.7
XS Rating Curve= 0
Exp/Cntr=0.5,0.3

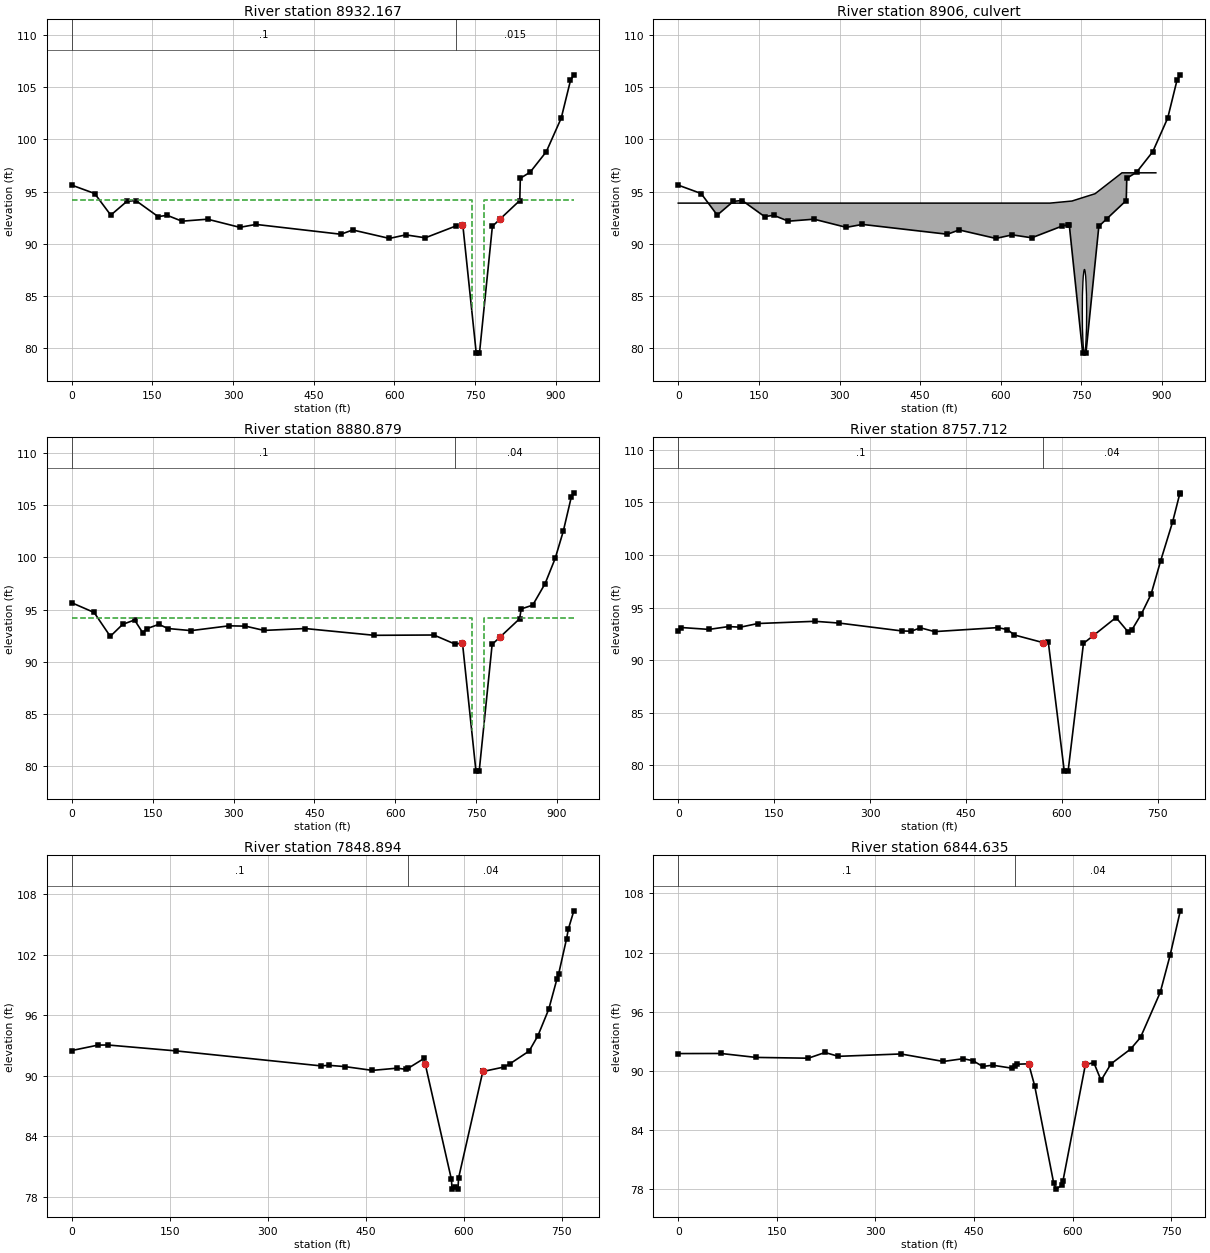
Type RM Length L Ch R = 1 ,8932.167,51.28,51.29,51.28
BEGIN DESCRIPTION:
Sta. 8932: Survey Data from Sta. 8984.57 used, adjusted for slope
END DESCRIPTION:
XS GIS Cut Line= 4
     3027708.385    13848012.585     3027710.405    13847862.116
     3027719.102    13847258.159     3027721.685    13847078.788
#Sta/Elev= 30
       0   95.62   42.54   94.82   72.55   92.75  102.55   94.07     119   94.15
  160.54   92.61  177.55   92.73   204.9   92.17  252.56   92.36  312.57   91.58
  342.57   91.86  500.67   90.92  522.59   91.33   590.8   90.52  621.25   90.86
   657.6   90.58  713.94    91.7  725.72   91.82  727.31   91.83  752.32   79.55
  758.35   79.54  782.36   91.68  797.21    92.4  833.33   94.15  834.34   96.28
  852.62   96.86  882.63   98.82  910.44  102.04  927.63  105.64  933.89  106.18
#Mann= 2 ,-1 , 0
       0      .1       0  713.94    .015       0
#XS Ineff= 2 , 0
       0  744.11    94.2  767.11       0    94.2
Permanent Ineff=
       F       F
Bank Sta=725.72,797.21
XS Rating Curve= 0
Exp/Cntr=0.5,0.3

Type RM Length L Ch R = 2 ,8906    ,,,
BEGIN DESCRIPTION:
Structure 1: Bridge/Culvert @ Addicks-Clodine
END DESCRIPTION:
Bridge Culvert--1,0,-1,-1, 0
Deck Dist Width WeirC Skew NumUp NumDn MinLoCord MaxHiCord MaxSubmerge Is_Ogee
7.5,37,2.6,0, 6, 6, , , 0.95, 0, 0,0,,
       0  691.37  732.37  775.37  825.37  888.37
    93.9    93.9    94.1    94.8    96.8    96.8
       0       0       0       0       0       0
       0  688.63  729.63  772.63  822.63  885.63
    93.9    93.9    94.1    94.8    96.8    96.8
       0       0       0       0       0       0
BR Coef=-1 , 1 , 1 ,1.25, 0 ,,,0.8,0,2,0,
WSPro=,,,, 1 ,,,, 0 ,,,, 0 ,,,,-1 ,-1 ,-1 , 0 , 0 , 0 , 0 , 0
Culvert=1,8,,37,0.015,0.5,1,1,1,79.54,755.61,79.52,752.73,Culvert #1  , 0 ,7.5
Culvert Bottom n=0.015
BC Design=,, 0 ,, 0 ,,,,,,
BC HTab HWMax=106.18

Type RM Length L Ch R = 1 ,8880.879,123.94,123.17,123.18
BEGIN DESCRIPTION:
Sta.  8881: Survey Data from Sta. 8984.57 used, adjusted for slope
END DESCRIPTION:
XS GIS Cut Line= 4
     3027758.583    13848011.451     3027761.676     13847863.11
     3027770.364    13847259.789     3027772.947    13847080.419
#Sta/Elev= 30
       0   95.65   41.42   94.72   71.42   92.43   94.41   93.58  116.43      94
  131.44   92.79  139.39   93.17  161.44   93.58   178.6   93.18  221.45   92.98
  291.66   93.44   322.1   93.41  356.46      93  432.85   93.18  561.18   92.53
  671.49   92.56   711.2   91.68  724.56   91.81  749.58   79.52  755.61   79.51
  779.62   91.66  794.47   92.37  830.59   94.12  833.51   95.06  854.83   95.42
  877.87   97.49  896.52    99.9  911.52   102.5  926.52  105.81  931.15  106.19
#Mann= 2 ,-1 , 0
       0      .1       0   711.2     .04       0
#XS Ineff= 2 , 0
       0   741.7    94.2   763.7       0    94.2
Permanent Ineff=
       F       F
Bank Sta=724.56,794.47
XS Rating Curve= 0
Exp/Cntr=0.5,0.3

Type RM Length L Ch R = 1 ,8757.712,909.01,908.82,909.66
BEGIN DESCRIPTION:
Sta. 8757: Survey Data from Sta. 8984.57 used, adjusted for slope
END DESCRIPTION:
XS GIS Cut Line= 3
     3027884.743    13847869.713     3027893.471    13847263.649
     3027896.054    13847084.278
#Sta/Elev= 30
       0   92.76    4.67   93.11   48.12   92.93   78.79    93.2   97.07   93.14
  124.68   93.49  213.98    93.7  252.11   93.53  350.33   92.78  364.71   92.76
  378.88   93.08  401.22   92.72  499.72    93.1  514.72   92.92  525.94    92.4
  571.07   91.67  578.94   91.75  603.95   79.46  609.98   79.45  633.99    91.6
  649.62   92.35  684.96   94.06  703.41   92.72  709.74   92.88  724.74   94.41
  739.75   96.27  754.75   99.45  773.42  103.14  784.75  105.85  785.52  105.92
#Mann= 2 ,-1 , 0
       0      .1       0  571.07     .04       0
Bank Sta=571.07,649.62
XS Rating Curve= 0
Exp/Cntr=0.3,0.1

Type RM Length L Ch R = 1 ,7848.894,1005.44,1004.26,1003.33
BEGIN DESCRIPTION:
Sta. 7849
END DESCRIPTION:
XS GIS Cut Line= 2
     3028787.253    13847875.267       3028806.5    13847106.626
#Sta/Elev= 30
       0   92.52   40.24   93.06   55.24   93.07  160.27   92.48  381.21      91
  393.93   91.05  417.82   90.93  460.37   90.55  498.01   90.77  512.35   90.65
  515.15   90.76  539.37   91.73  541.29   91.18   581.4   79.73   582.4   78.77
  586.38   79.02   591.4   78.77  592.35   79.87  629.46   90.44  630.48   90.45
  661.63   90.88  670.43   91.18  700.44   92.47  713.86   93.99  730.45   96.62
  743.14   99.65  745.46  100.08  757.77  103.62  760.46  104.57  768.88  106.38
#Mann= 2 ,-1 , 0
       0      .1       0  515.15     .04       0
Bank Sta=541.29,630.48
XS Rating Curve= 0
Exp/Cntr=0.3,0.1

Type RM Length L Ch R = 1 ,6844.635,854.71,855.91,856.93
BEGIN DESCRIPTION:
Sta. 6845
END DESCRIPTION:
XS GIS Cut Line= 2
     3029801.283    13847893.311     3029807.297    13847129.481
#Sta/Elev= 30
       0   91.75   65.01   91.76  118.27   91.36  197.93   91.28  223.27   91.86
  243.61   91.47  338.69   91.71  403.28   90.95  433.28   91.23  448.28   91.03
  463.28   90.44  478.28   90.57  508.28   90.26  511.78   90.47  515.25   90.67
  533.17   90.71   542.3   88.47  571.31   78.57  575.32   77.99  583.31   78.39
  585.31   78.82  619.49   90.65  632.34   90.82  643.29   89.03  658.29    90.7
  688.29   92.21  703.29   93.39  733.29   97.96  748.29  101.72  763.85  106.24
#Mann= 2 ,-1 , 0
       0      .1       0  511.78     .04       0
Bank Sta=533.17,619.49
XS Rating Curve= 0
Exp/Cntr=0.3,0.1