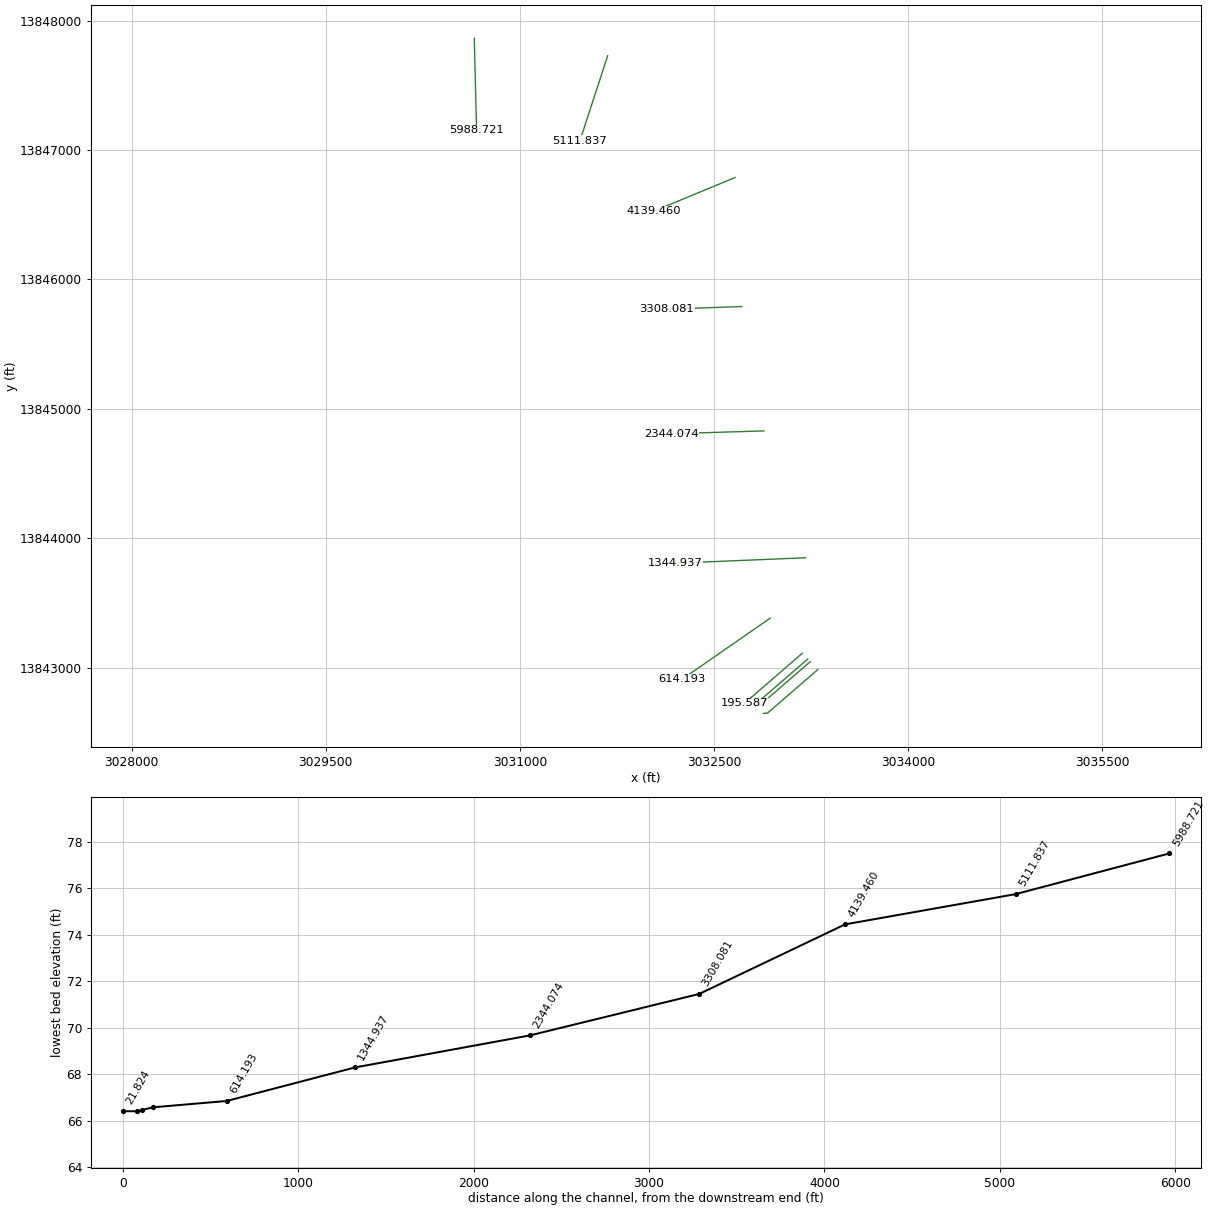
HEC-RAS study W170-00-00.prj: W170-00-00

--- W170-00-00.g01 (geometry) --- (continued)

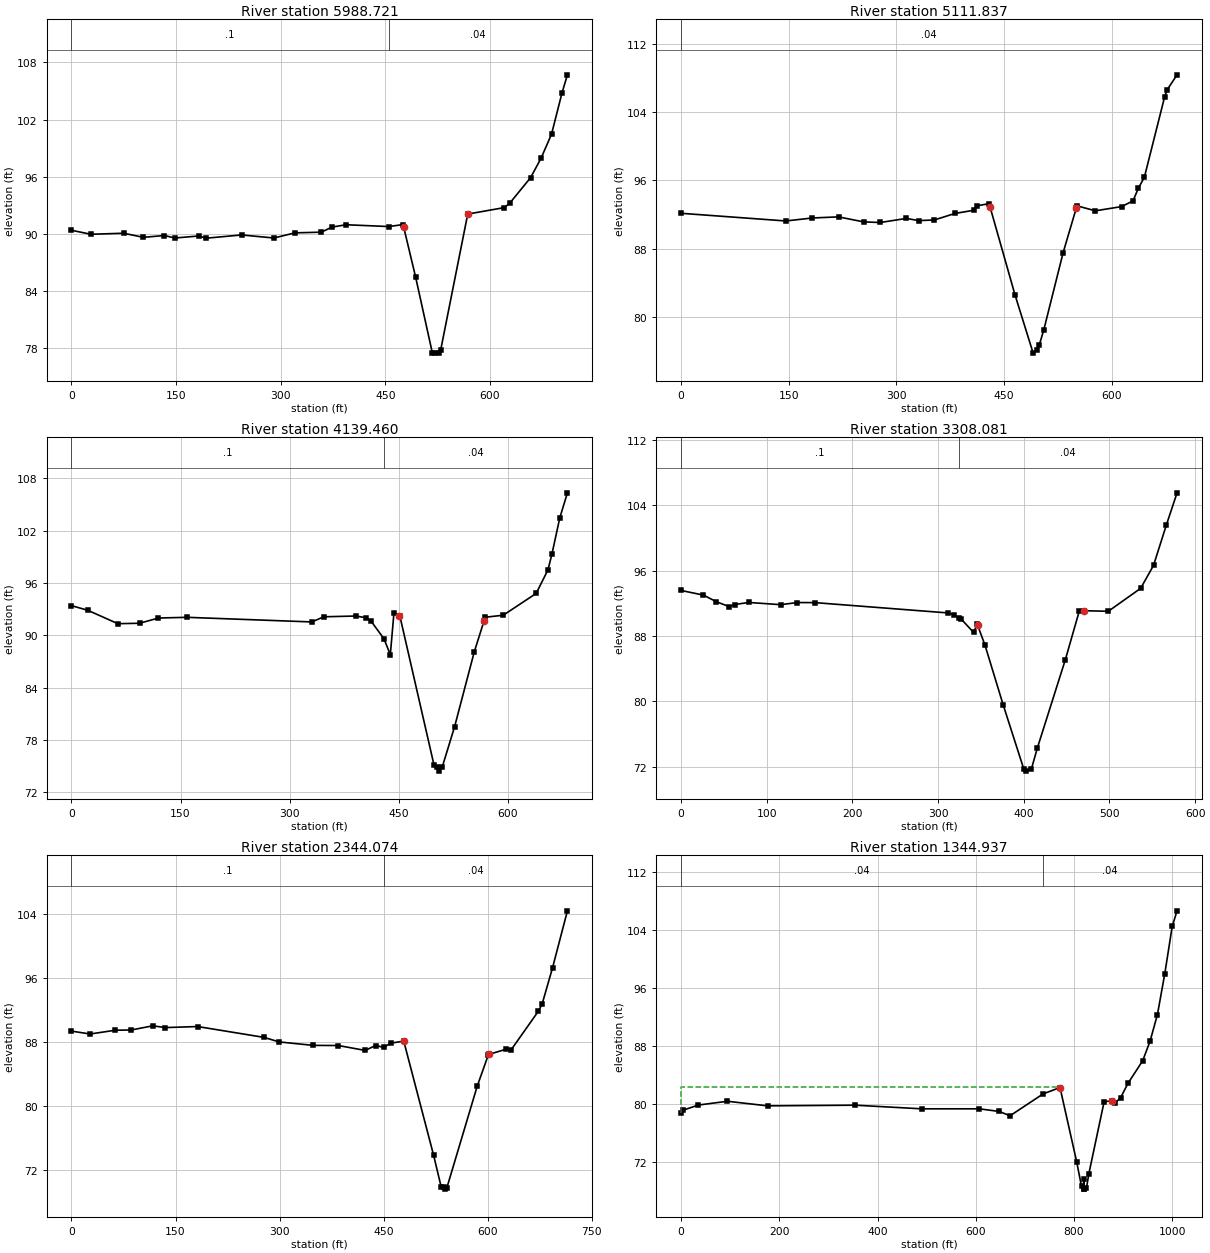
Type RM Length L Ch R = 1 ,5988.721,903.89,876.88,848.57
BEGIN DESCRIPTION:
Sta. 5989
END DESCRIPTION:
XS GIS Cut Line= 2
     3030648.111    13847863.239     3030666.155    13847152.336
#Sta/Elev= 30
       0   90.38   27.92   89.96   74.69   90.07  103.23   89.64  133.24   89.83
  148.24   89.57  182.46   89.78  193.26   89.55  244.04   89.89  290.23   89.57
  320.59   90.11  358.31   90.18  373.32   90.71  393.75   90.96  455.12   90.77
  475.46   90.98  476.46   90.68  493.41   85.49  517.37   77.54  521.37   77.49
  526.35    77.5  529.34   77.79  568.19   92.08  620.73   92.76   628.4   93.22
  658.41   95.91  673.41   97.95  688.42  100.48  703.42  104.81  711.13  106.69
#Mann= 2 ,-1 , 0
       0      .1       0  455.12     .04       0
Bank Sta=476.46,568.19
XS Rating Curve= 0
Exp/Cntr=0.3,0.1

Type RM Length L Ch R = 1 ,5111.837,1039.94,972.38,897.41
BEGIN DESCRIPTION:
Sta. 5112
END DESCRIPTION:
XS GIS Cut Line= 2
     3031678.981    13847728.516     3031464.868    13847071.743
#Sta/Elev= 30
       0   92.15  145.78   91.25  182.89    91.6  219.27   91.73  254.31   91.14
   277.3   91.07  313.93   91.55  330.81   91.29  352.87   91.37  381.34   92.13
  408.59   92.52  412.21   93.03  428.97   93.28  430.36   92.88  465.06   82.58
  490.34   75.74  495.71   76.12  498.87   76.69   505.2   78.48  532.09   87.53
  550.56    92.8  551.37   93.03  576.98   92.44   613.7   92.94  629.47   93.61
  636.75   95.07  645.25   96.38  673.37  105.78   676.8  106.62  690.79   108.4
#Mann= 1 ,-1 , 0
       0     .04       0
Bank Sta=430.36,550.56
XS Rating Curve= 0
Exp/Cntr=0.3,0.1

Type RM Length L Ch R = 1 ,4139.460,860.44,831.38,796.74
BEGIN DESCRIPTION:
Sta. 4139
END DESCRIPTION:
XS GIS Cut Line= 2
     3032664.141    13846787.862     3032033.831    13846526.837
#Sta/Elev= 30
       0   93.41    22.3   92.88   63.85   91.34   93.72   91.39  119.72   91.99
  159.02   92.07  330.77   91.54  347.01   92.13  391.41   92.22  405.67   92.01
  411.95   91.65   429.8   89.62  438.61   87.79  443.52   92.51  450.95   92.26
  451.67   92.24  498.83   75.09  502.91   74.91  505.14   74.44  510.14   74.94
  527.06   79.54  553.98   88.08  567.61   91.68  569.15   92.08  593.91   92.31
  639.25   94.81  655.48   97.52  660.86    99.3  671.72  103.47  682.22  106.34
#Mann= 2 ,-1 , 0
       0      .1       0   429.8     .04       0
Bank Sta=450.95,567.61
XS Rating Curve= 0
Exp/Cntr=0.3,0.1

Type RM Length L Ch R = 1 ,3308.081,964.43,964.01,963.43
BEGIN DESCRIPTION:
Sta. 3308
END DESCRIPTION:
XS GIS Cut Line= 2
     3032714.662    13845790.674     3032136.076    13845770.225
#Sta/Elev= 30
       0   93.58   26.14   93.01   41.15    92.2   56.16    91.6   62.75   91.86
   79.02   92.11   116.2   91.84  135.79    92.1  156.28   92.09  311.32   90.83
  318.52   90.61  324.21   90.23  327.26   90.04  341.34   88.45  345.61   89.46
  346.21   89.29  354.71   86.89  375.84   79.61  399.86   71.76  402.89   71.45
  408.89    71.7  415.85   74.28  448.51   85.09  464.94   91.11  470.11    91.1
  498.67   91.03  536.46   93.84  551.47   96.65  566.48  101.61  578.95  105.54
#Mann= 2 ,-1 , 0
       0      .1       0  324.21     .04       0
Bank Sta=346.21,470.11
XS Rating Curve= 0
Exp/Cntr=0.3,0.1

Type RM Length L Ch R = 1 ,2344.074,998.15,999.14,1000.2
BEGIN DESCRIPTION:
Sta. 2344
END DESCRIPTION:
XS GIS Cut Line= 2
     3032886.674    13844829.571     3032172.163    13844807.919
#Sta/Elev= 30
       0   89.39   26.87   89.03   63.38    89.5   86.26   89.53  117.22   90.05
  135.49   89.83  181.88   89.96   277.3   88.61  299.41   88.04   348.3   87.61
  384.75   87.59  423.33   86.98  438.34   87.59  450.35   87.36  459.87   87.88
  478.94   88.14  521.91   73.92  532.99   69.91  536.99   69.88  538.99   69.67
  541.02   69.82  584.94   82.55  601.05   86.47  601.89   86.49  626.86   87.14
  633.43   87.02  673.02   91.88  678.45   92.79  693.46   97.31  714.84   104.4
#Mann= 2 ,-1 , 0
       0      .1       0  450.35     .04       0
Bank Sta=478.94,601.89
XS Rating Curve= 0
Exp/Cntr=0.3,0.1

Type RM Length L Ch R = 1 ,1344.937,681.66,730.74,774.14
BEGIN DESCRIPTION:
Sta. 1345
END DESCRIPTION:
XS GIS Cut Line= 2
     3033207.844    13843849.223     3032198.626    13843807.122
#Sta/Elev= 30
       0   78.82    3.82   79.17   35.24   79.88   94.31    80.4  176.04   79.77
  354.62   79.86  489.73   79.36  607.09   79.36  647.69      79  669.89    78.4
  737.37   81.42  771.71   82.29  805.53   72.09  815.52   68.66  819.56   68.35
  820.02   69.69  821.56   68.29  825.55   68.43  830.51   70.44  861.56   80.34
  877.77   80.46  882.69    80.1  895.09   80.88   910.1   82.87  940.13   85.99
  955.14   88.69  970.15   92.36  985.17   98.01 1000.18  104.49  1010.1  106.65
#Mann= 2 ,-1 , 0
       0     .04       0  737.37     .04       0
#XS Ineff= 2 , 0
       0  772.39    82.3               0
Permanent Ineff=
       F       F
Bank Sta=771.71,877.77
XS Rating Curve= 0
Exp/Cntr=0.3,0.1

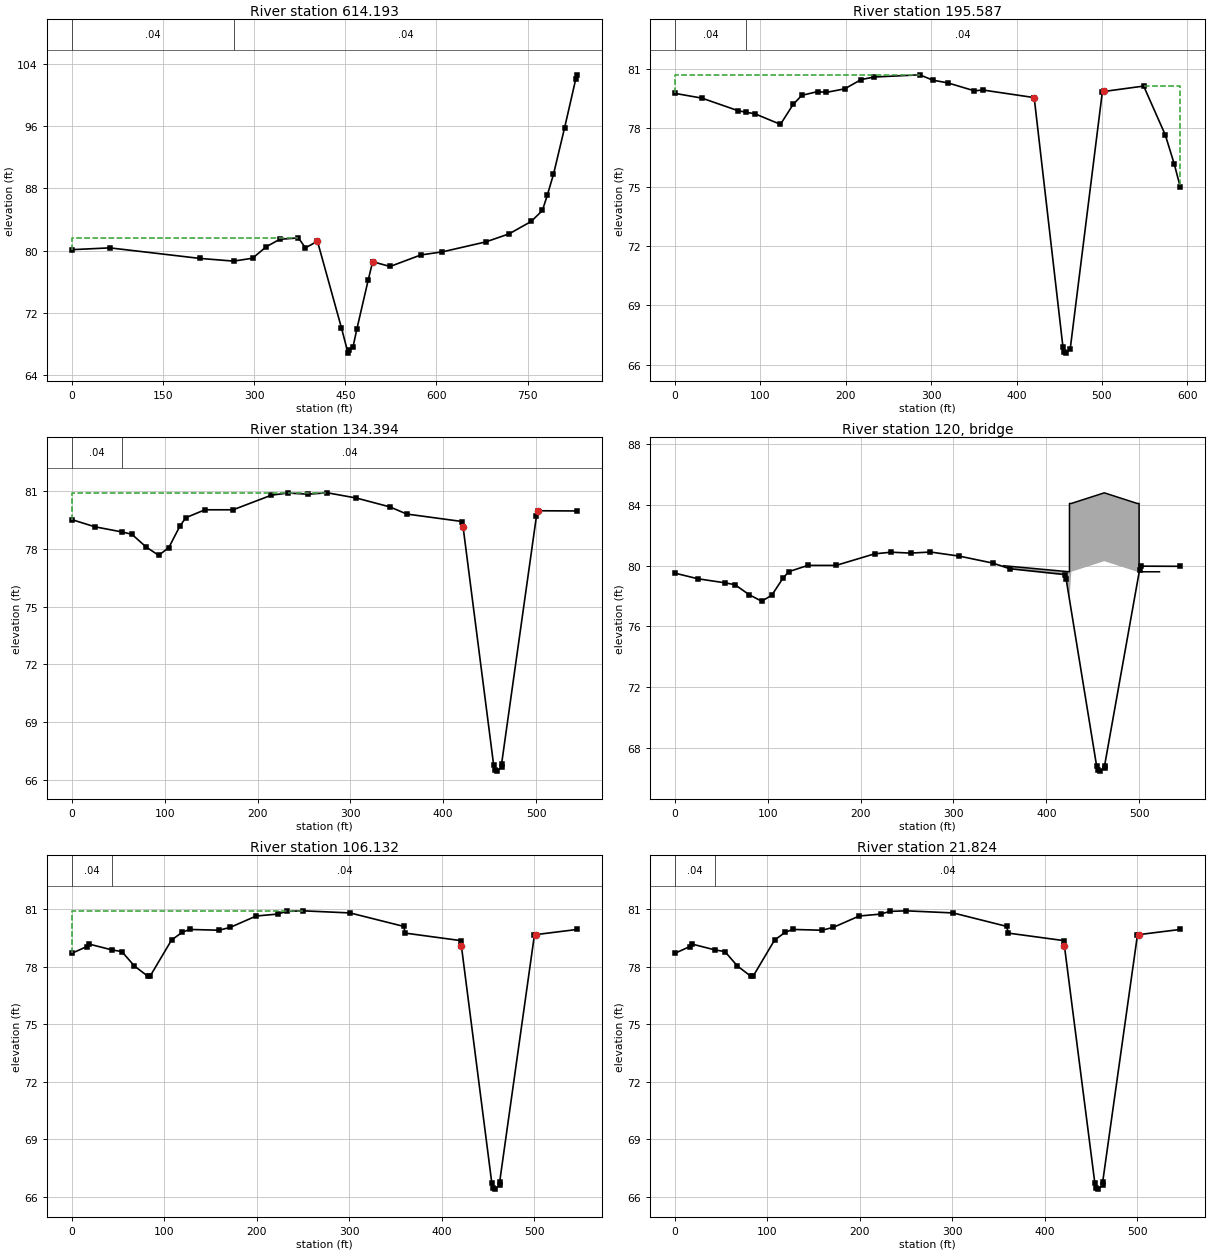
Type RM Length L Ch R = 1 ,614.193 ,407.85,418.61,425.11
BEGIN DESCRIPTION:
Sta. 614
END DESCRIPTION:
XS GIS Cut Line= 2
     3032934.789    13843382.504     3032251.553    13842908.569
#Sta/Elev= 30
       0   80.13   62.38   80.36  210.08   79.01  266.09   78.66  297.29   79.03
  320.13   80.52  342.16   81.46  372.76   81.64  384.33   80.36  404.12   81.21
  443.65   70.08  454.47   66.85  456.68   67.31   462.5   67.59  469.14      70
  487.74   76.26  494.95   78.58  495.59   78.57  523.64   77.97  574.21   79.45
  609.87   79.85  681.41   81.13  719.57   82.16  756.09   83.76  774.34   85.16
  782.33   87.09   792.6    89.8  810.85   95.76  829.11  101.98  831.52  102.57
#Mann= 2 ,-1 , 0
       0     .04       0  266.09     .04       0
#XS Ineff= 2 , 0
       0  372.72   81.64               0
Permanent Ineff=
       F       F
Bank Sta=404.12,495.59
XS Rating Curve= 0
Exp/Cntr=0.3,0.1

Type RM Length L Ch R = 1 ,195.587 ,61.12,61.19,49.81
BEGIN DESCRIPTION:
Sta. 196
END DESCRIPTION:
XS GIS Cut Line= 3
     3033182.504    13843110.574     3032835.198    13842810.201
     3032735.036    13842723.625
#Sta/Elev= 30
       0   79.74   31.55    79.5   74.09   78.86   82.82   78.79      94    78.7
  123.52   78.17  138.39   79.18  148.53   79.64  167.11   79.83  177.12   79.79
  198.82   79.97  217.97   80.44   233.6   80.57  286.77   80.68  301.87   80.41
  319.68   80.27  350.58   79.87   360.7   79.91  420.02   79.53  420.66   79.52
  454.27   66.91  455.68   66.65  457.84   66.58  462.83   66.79  500.47   79.82
  502.84   79.84  548.86   80.11  574.11   77.64  584.54   76.18  591.57   75.02
#Mann= 2 ,-1 , 0
       0     .04       0   82.82     .04       0
#XS Ineff= 2 , 0
       0  286.77   80.68  548.86       0   80.11
Permanent Ineff=
       F       F
Bank Sta=420.02,502.84
XS Rating Curve= 0
Exp/Cntr=0.5,0.3

Type RM Length L Ch R = 1 ,134.394 ,28.24,28.26,27.75
BEGIN DESCRIPTION:
Sta. 134: Survey data from Sta. 195.6 used, adjusted for slope
END DESCRIPTION:
XS GIS Cut Line= 4
     3033224.607    13843066.175     3032877.301    13842765.802
     3032838.901     13842732.26     3032805.505    13842725.497
#Sta/Elev= 28
       0   79.51   24.59   79.14   54.16   78.87   64.58   78.75   79.97   78.09
   93.45   77.66  104.36   78.06  116.38   79.18   122.7   79.61  143.25   80.02
  173.56   80.02  214.97   80.78  232.79   80.89  253.96   80.83  275.27    80.9
  306.42   80.63  342.54   80.17   360.7    79.8  420.66   79.41  421.39   79.13
  454.27    66.8  455.68   66.54  457.85   66.47  462.83   66.68  462.83   66.83
  500.47   79.71   502.1   79.97  544.24   79.96
#Mann= 2 ,-1 , 0
       0     .04       0   54.16     .04       0
#XS Ineff= 2 , 0
       0  275.27    80.9               0
Permanent Ineff=
       F       F
Bank Sta=421.39,502.1
XS Rating Curve= 0
Exp/Cntr=0.5,0.3

Type RM Length L Ch R = 3 ,120     ,,,
BEGIN DESCRIPTION:
Structure 2: Foot Bridge Near Confluence w/ Buffalo Bayou
END DESCRIPTION:
Bridge Culvert--1,0,-1,-1, 0
Deck Dist Width WeirC Skew NumUp NumDn MinLoCord MaxHiCord MaxSubmerge Is_Ogee
10,8,2.6,0, 9, 9, , , 0.95, 0, 0,0,,
     354     425     425     427   462.5     498     500     500     522
      80    79.6    84.1    84.1    84.8    84.1    84.1    79.6    79.6
       0       0       0    79.6    80.3    79.6       0       0       0
     354     425     425     427   462.5     498     500     500     522
      80    79.6    84.1    84.1    84.8    84.1    84.1    79.6    79.6
       0       0       0    79.6    80.3    79.6       0       0       0
BR Coef=-1 , 1 , 0 ,1.25, 0 ,,,0.8,0,2,0,
WSPro=,,,, 1 ,,,, 0 ,,,, 0 ,,,,-1 ,-1 ,-1 , 0 , 0 , 0 , 0 , 0
BC Design=,, 0 ,, 0 ,,,,,,
BC HTab HWMax=80.9

Type RM Length L Ch R = 1 ,106.132 ,84.226,84.312,82.726
BEGIN DESCRIPTION:
Sta. 106: Survey data from Sta. 195.6 used, adjusted for slope
END DESCRIPTION:
XS GIS Cut Line= 4
     3033243.956    13843045.575      3032896.65    13842745.202
     3032855.487    13842709.138     3032822.837    13842706.474
#Sta/Elev= 30
       0   78.69    16.1   79.04    18.4   79.17   43.73   78.86      54   78.78
   67.55   78.03   82.21   77.49   84.89   77.52  107.82   79.38  119.55   79.79
  127.63   79.93  159.21   79.89  171.39   80.04  199.36   80.63  222.47   80.73
  232.46   80.87  250.34    80.9  301.01   80.79  358.96   80.09   360.7   79.74
  420.66   79.35  421.43   79.07  454.27   66.75  455.68   66.49  457.85   66.41
  462.83   66.62  462.83   66.78  500.47   79.65  501.78   79.66  546.66   79.93
#Mann= 2 ,-1 , 0
       0     .04       0   43.73     .04       0
#XS Ineff= 2 , 0
       0  250.34    80.9               0
Permanent Ineff=
       F       F
Bank Sta=421.43,501.78
XS Rating Curve= 0
Exp/Cntr=0.5,0.3

Type RM Length L Ch R = 1 ,21.824  ,32.83,21.82,20.48
BEGIN DESCRIPTION:
Sta. 106: Survey data from Sta. 195.6 used, adjusted for slope
Cross-section copied from upstream cross-section to aid in tying in floodway delineation.
END DESCRIPTION:
XS GIS Cut Line= 4
     3033303.668    13842985.863     3032956.362     13842685.49
     3032915.199    13842649.426     3032882.549    13842646.762
#Sta/Elev= 30
       0   78.69    16.1   79.04    18.4   79.17   43.73   78.86      54   78.78
   67.55   78.03   82.21   77.49   84.89   77.52  107.82   79.38  119.55   79.79
  127.63   79.93  159.21   79.89  171.39   80.04  199.36   80.63  222.47   80.73
  232.46   80.87  250.34    80.9  301.01   80.79  358.96   80.09   360.7   79.74
  420.66   79.35  421.43   79.07  454.27   66.75  455.68   66.49  457.85   66.41
  462.83   66.62  462.83   66.78  500.47   79.65  501.78   79.66  546.66   79.93
#Mann= 2 ,-1 , 0
       0     .04       0   43.73     .04       0
Bank Sta=421.43,501.78
XS Rating Curve= 0
Exp/Cntr=0.3,0.1

Chan Stop Cuts=-1